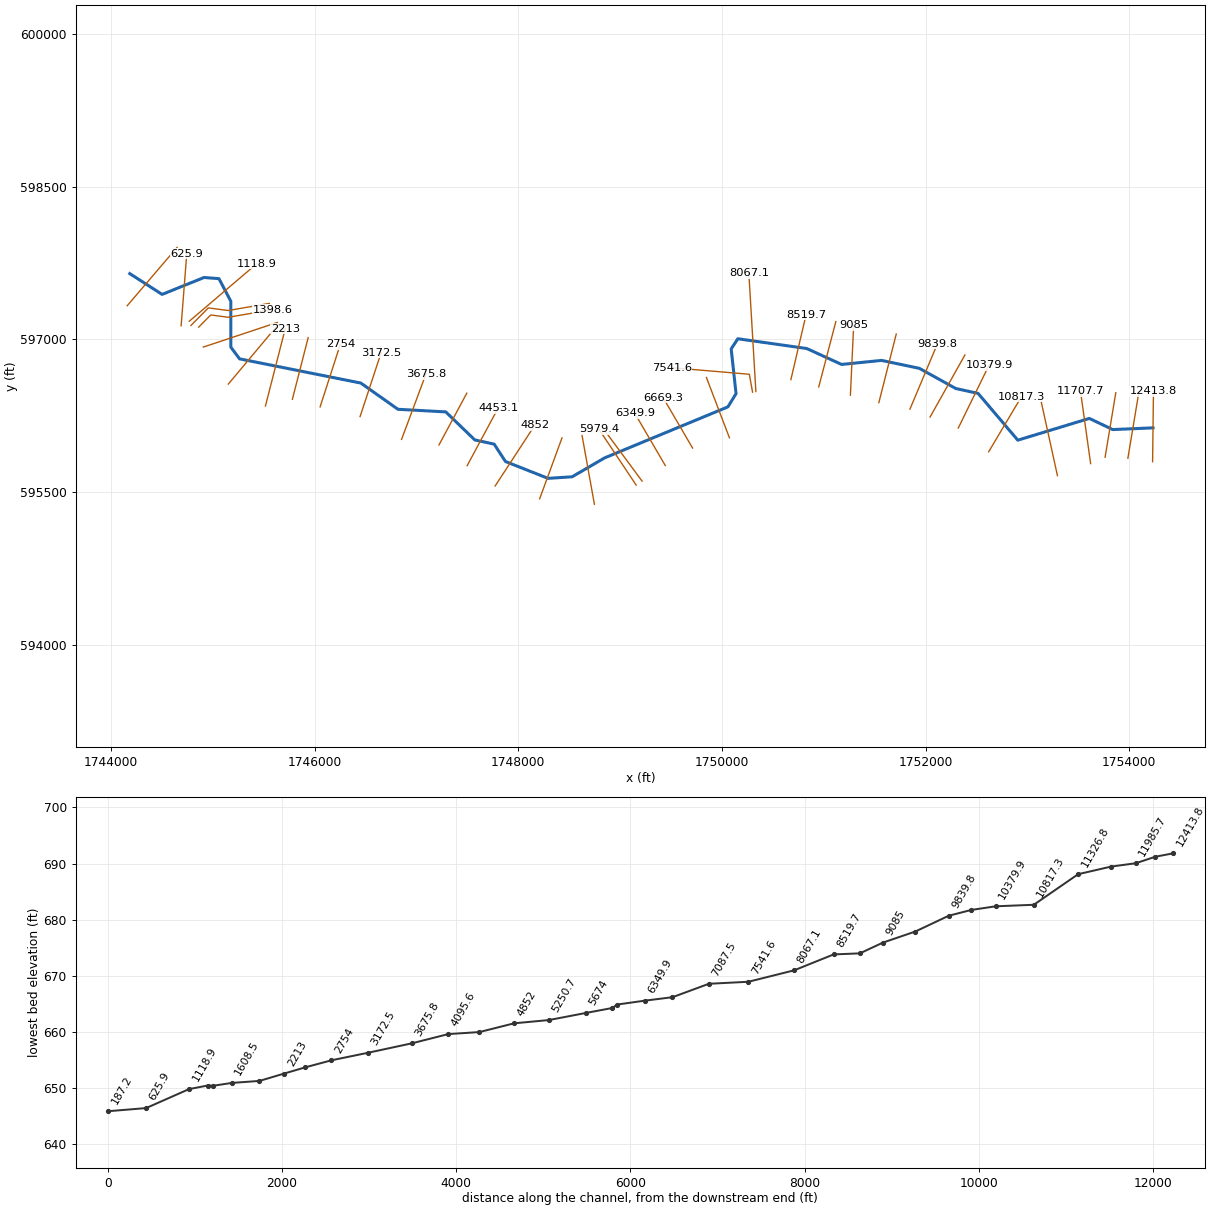
--- ClendeninC.prj (project) ---

Proj Title=ClendeninC
Current Plan=p01
Default Exp/Contr=0,0
English Units
Geom File=g01
Flow File=f01
Plan File=p01
BEGIN DESCRIPTION:
AMEC Environment & Infrastructure, 2013
Projection: NAD 1983 State Plane West Virginia South FIPS 4702 (US Feet)
Vertical Datum: NAVD 1988
END DESCRIPTION:
DSS Export Rating Curves= 0
DSS Export Rating Curve Sorted= 0
DSS Export Volume Flow Curves= 0
DXF OffsetX= 0
DXF OffsetY= 0
DXF ScaleX= 0
DXF ScaleY= 0

--- ClendeninC.p01 (plan) ---

Plan Title=Floodplain
Program Version=4.00
Geom File=g01
Flow File=f01
K Sum by GR=0
Std Step Tol=0.01
Critical Tol=0.01
Num of Std Step Trials=20
Max Error Tol=0.3
Flow Tol Ratio=0.001
Split Flow NTrial=30
Split Flow Tol=0.02
Split Flow Ratio=0.02
Log Output Level=0
Friction Slope Method=1
Unsteady Friction Slope Method=2
Unsteady Bridges Friction Slope Method=1
Global Log Level=0
CheckData=False
Run HTab=0
Run UNet=0
Run PostProcess=0
UNET Theta=0
UNET Theta Warmup=0
UNET ZTol=0
UNET ZSATol=0
UNET MxIter=0
UNET MaxInSteps=0
UNET DtIC=0
UNET DtMin=0
UNET MaxCRTS=0
UNET WFStab=0
UNET SFStab=0
UNET WFX=0
UNET SFX=0
UNET DSS MLevel=0
UNET DZMax Abort=0
UNET Convert EG Bridges=0
UNET Use Existing IB Tables=0
UNET Froude Limit=0
UNET Froude Power=0
Write IC File=0
Echo Input=False
Echo Output=False
Write Detailed=0

--- ClendeninC.f01 (steady flow) ---

Flow Title=USGS Regress. Eqn. (2010) - Western-Plateaus
Program Version=4.00
Number of Profiles=1
Profile Names=P100yr
River Rch & RM=ClendeninC,Main      ,12413.8
    1674
River Rch & RM=ClendeninC,Main      ,10096.3
    1711
River Rch & RM=ClendeninC,Main      ,8067.1
    1749
River Rch & RM=ClendeninC,Main      ,7087.5
    1816
River Rch & RM=ClendeninC,Main      ,6033.4
    1848
River Rch & RM=ClendeninC,Main      ,5250.7
    1899
River Rch & RM=ClendeninC,Main      ,3172.5
    1972
River Rch & RM=ClendeninC,Main      ,187.2
    2022
Boundary for River Rch & Prof#=ClendeninC,Main      ,1
Up Type=0
Dn Type=3
Dn Slope=0.003703

--- ClendeninC.g01 (geometry) ---

Geom Title=USGS 3m DEM
Program Version=4.10

River Reach=ClendeninC      ,Main
Reach XY= 30
     1754233.904      596132.213      1753838.19      596115.645
     1753608.155       596225.02     1752905.898      596011.478
     1752516.105      596470.289     1752295.951      596518.892
     1751939.022      596716.383     1751567.147      596794.247
     1751174.959      596754.664     1750833.032      596910.914
     1750156.328      597006.587     1750090.703      596907.108
     1750138.698      596467.629     1750058.229      596338.201
     1748846.658      595837.044     1748528.689      595652.148
     1748292.014      595636.892     1747874.009      595802.067
     1747762.898       595972.64     1747572.794      596013.872
     1747287.637      596289.046     1746818.358      596314.516
     1746453.684      596571.736     1745262.319      596809.562
     1745176.208      596925.187     1745176.527      597374.823
     1745059.872      597596.503     1744913.605      597607.787
     1744501.604      597441.989     1744183.914      597645.972

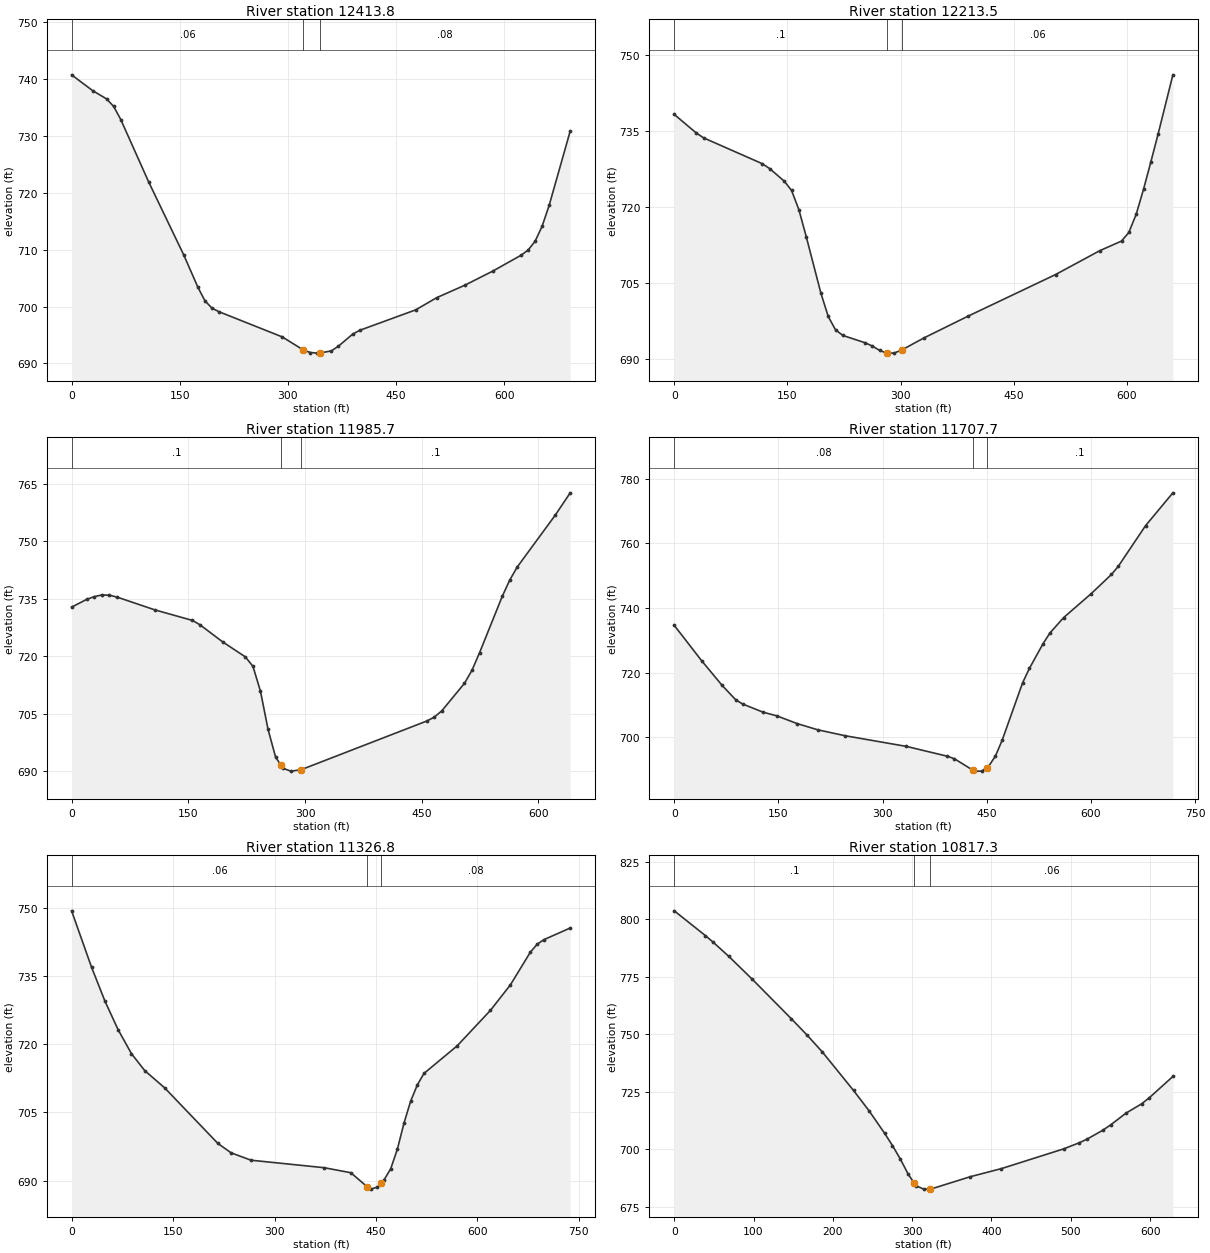
Type RM Length L Ch R = 1 ,12413.8 ,204.4,200.3,196.2
XS GIS Cut Line= 2
     1754229.838      595800.711     1754238.318      596492.159
#Sta/Elev= 30
       0  740.78    29.2     738    48.7  736.53    58.4  735.21    68.2  732.91
   107.1  721.88   155.8  709.02   175.3  703.37     185  701.01   194.8  699.72
   204.5   699.1   292.2  694.67   321.5  692.36   331.1  691.93   340.9  691.82
     344 691.831   360.4  692.22   370.1  693.05   389.6  695.14   399.3  695.82
   477.2  699.43   506.4  701.58   545.4  703.77   584.4  706.27   623.3  709.04
   633.1  709.95   642.8   711.5   652.5  714.13   662.3  717.82   691.5  730.89
#Mann= 3 , 0 , 0
       0     .06       0   321.5    .045       0     344     .08       0
Bank Sta=321.5,344
XS Rating Curve= 0 ,0
Exp/Cntr=0.3,0.1

Type RM Length L Ch R = 1 ,12213.5 ,227,227.8,227.2
XS GIS Cut Line= 2
     1753986.976      595834.189     1754095.469      596486.195
#Sta/Elev= 30
       0   738.3    29.2  734.64    38.9  733.68   116.6  728.59   126.4  727.63
   145.8  725.14   155.5  723.31   165.2  719.52     175  714.17   194.4  703.05
   204.1  698.46   213.8  695.82   223.6  694.71   252.7  693.29   262.4  692.64
   272.2  691.77   281.7  691.23   291.6  691.25   301.7  691.86   330.5  694.19
   388.8  698.47   505.4  706.72   563.8  711.41   592.9  713.33   602.6  715.02
   612.4  718.63   622.1  723.55   631.8  728.93   641.5  734.48     661  746.11
#Mann= 3 , 0 , 0
       0      .1       0   281.7    .045       0   301.7     .06       0
Bank Sta=281.7,301.7
XS Rating Curve= 0 ,0
Exp/Cntr=0.3,0.1

Type RM Length L Ch R = 1 ,11985.7 ,269.9,278.1,285.3
XS GIS Cut Line= 2
      1753763.17      595844.506     1753868.369      596476.715
#Sta/Elev= 30
       0  732.81    19.4  734.83    29.1  735.55    38.8  735.98    48.6  735.92
    58.3  735.44   106.8  732.11   155.4  729.34   165.1   728.2   194.2  723.75
   223.3  719.85   233.1  717.38   242.8  710.86   252.5  700.96   262.2  693.71
   269.3691.5652   271.8  690.81   281.6  690.06   294.3690.3758   456.4  703.11
   466.1  704.12   475.8  705.77     505  712.96   514.7  716.37   524.4  720.94
   553.5   735.6   563.2  739.89   572.9   743.3   621.5  756.74   640.9  762.61
#Mann= 3 , 0 , 0
       0      .1       0   269.3    .045       0   294.3      .1       0
Bank Sta=269.3,294.3
XS Rating Curve= 0 ,0
Exp/Cntr=0.3,0.1

Type RM Length L Ch R = 1 ,11707.7 ,377.9,380.8,381.8
XS GIS Cut Line= 2
     1753621.207      595781.397     1753521.409      596492.412
#Sta/Elev= 30
       0   734.6    39.3  723.69    68.8  716.05    88.5  711.56    98.4  710.27
   127.9  707.72   147.5  706.61     177  704.19   206.5  702.28   245.9  700.44
   334.4  697.13   393.4  694.08   403.2  693.34   429.8   689.8   432.8  689.48
   442.6  689.48   449.8  690.52   452.4  690.89   462.3  694.08   472.1  698.99
   501.6  716.82   511.4  721.28   531.1  728.96     541  732.25   560.6  736.99
     600  744.35   629.5  750.35   639.3  752.85   678.6  765.45     718  775.63
#Mann= 3 , 0 , 0
       0     .08       0   429.8    .045       0   449.8      .1       0
Bank Sta=429.8,449.8
XS Rating Curve= 0 ,0
Exp/Cntr=0.3,0.1

Type RM Length L Ch R = 1 ,11326.8 ,527.8,509.5,489.5
XS GIS Cut Line= 2
     1753295.337      595663.004     1753137.145      596383.066
#Sta/Elev= 30
       0  749.35    29.5  736.94    49.2  729.52    68.8  723.19    88.5  717.93
   108.1   714.2   137.6   710.4   216.3  698.17   235.9   696.1   265.4  694.48
   373.5  692.83   412.8  691.73   437.2  688.62   442.3  688.12   452.2  688.57
   457.2  689.39     462  690.17   471.8   692.6   481.7  696.93   491.5  702.68
   501.3  707.48   511.2  711.06     521  713.58   570.1  719.65   619.3  727.46
   648.8  733.07   678.3  740.26   688.1  741.96   697.9  742.98   737.2  745.57
#Mann= 3 , 0 , 0
       0     .06       0   437.2    .045       0   457.2     .08       0
Bank Sta=437.2,457.2
XS Rating Curve= 0 ,0
Exp/Cntr=0.3,0.1

Type RM Length L Ch R = 1 ,10817.3 ,435.6,437.4,439.5
XS GIS Cut Line= 2
     1752619.456      595897.304     1752941.349      596437.371
#Sta/Elev= 30
       0  803.59    39.3  792.81    49.1  789.95    68.8  783.79    98.2  773.92
   147.4  756.78     167  749.77   186.6  742.32     226  725.56   245.6  716.72
   265.2  706.95   275.1  701.61   284.9  695.85   294.7  689.35   302.7  685.16
   304.5  684.22   314.4  682.67   322.7  682.76   324.2  682.78   373.3  688.07
   412.6   691.6   491.2  700.18   510.8  702.83   520.7  704.43   540.3  708.25
   550.1  710.55   569.8  715.74   589.4  719.76   599.2  722.44   628.7  731.62
#Mann= 3 , 0 , 0
       0      .1       0   302.7    .045       0   322.7     .06       0
Bank Sta=302.7,322.7
XS Rating Curve= 0 ,0
Exp/Cntr=0.3,0.1

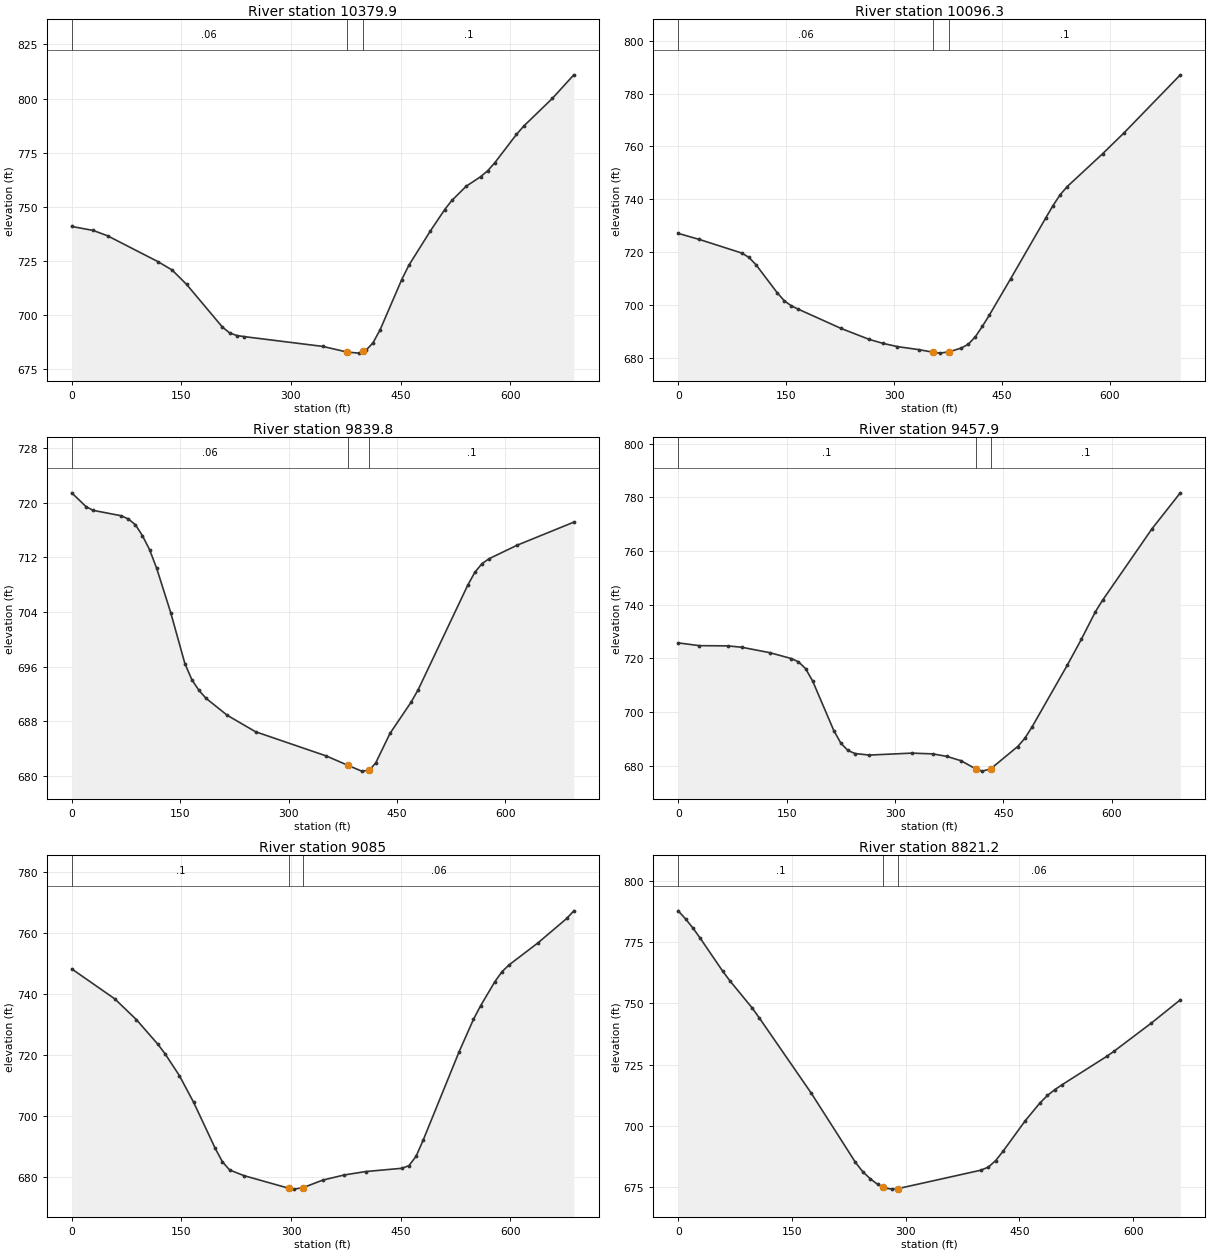
Type RM Length L Ch R = 1 ,10379.9 ,284.6,283.6,281.8
XS GIS Cut Line= 2
     1752321.436      596131.029     1752623.758      596748.139
#Sta/Elev= 30
       0  740.91    29.4  739.06    49.1  736.58   117.8  724.69   137.4  720.78
   157.1  714.17   206.2  694.43     216  691.76   225.8  690.54   235.6  690.04
   343.6   685.5   376.3  682.93   392.7   682.4   398.8683.1785   402.5  683.65
   412.3  687.16   422.1  693.25   451.6  716.35   461.4     723   490.8  738.82
   510.5  748.74   520.3  752.95   539.9   759.5   559.6   763.9   569.4  766.68
   579.2  770.42   608.6   783.4   618.5  787.23   657.7  800.03   687.2  810.95
#Mann= 3 , 0 , 0
       0     .06       0   376.3    .045       0   398.8      .1       0
Bank Sta=376.3,398.8
XS Rating Curve= 0 ,0
Exp/Cntr=0.3,0.1

Type RM Length L Ch R = 1 ,10096.3 ,253.1,256.6,258.8
XS GIS Cut Line= 2
     1752044.288      596238.982     1752386.377      596847.458
#Sta/Elev= 30
       0  727.08    29.5  724.77    88.5  719.62    98.3  717.98   108.2  715.18
   137.6   704.6   147.5  701.54   157.3  699.64   167.1  698.36   226.1  691.12
   265.4  686.95   285.1   685.4   304.8  684.21   334.3  683.07   353.9   682.1
   363.8  681.74   376.4682.2368   393.3  683.65   403.1  685.08   412.9  687.89
   422.8  691.88   432.6  696.18   462.1  709.89   511.2  733.05   521.1  737.63
   530.9  741.69   540.7  744.78   589.9  757.21   619.4  765.04     698  787.11
#Mann= 3 , 0 , 0
       0     .06       0   353.9    .045       0   376.4      .1       0
Bank Sta=353.9,376.4
XS Rating Curve= 0 ,0
Exp/Cntr=0.3,0.1

Type RM Length L Ch R = 1 ,9839.8  ,376,381.9,383.4
XS GIS Cut Line= 2
     1751846.569      596315.997     1752116.035      596956.271
#Sta/Elev= 30
       0  721.45    19.6  719.44    29.4  718.89    68.5  718.09    78.3  717.62
    88.1  716.78    97.8  715.17   107.6  713.14   117.4  710.43     137  703.88
   156.5  696.46   166.3  694.06   176.1  692.52   185.9  691.36   215.2  688.88
   254.4  686.47   352.2  682.93   381.7 681.575   401.2  680.71   411.7  680.83
   420.7  681.94   440.3  686.23   469.6  690.82   479.4  692.65   547.9  707.93
   557.7  709.81   567.5  711.07   577.3   711.8   616.4  713.79   694.7  717.16
#Mann= 3 , 0 , 0
       0     .06       0   381.7    .045       0   411.7      .1       0
Bank Sta=381.7,411.7
XS Rating Curve= 0 ,0
Exp/Cntr=0.3,0.1

Type RM Length L Ch R = 1 ,9457.9  ,367.4,372.9,377
XS GIS Cut Line= 2
     1751541.053      596379.874     1751712.129      597053.431
#Sta/Elev= 30
       0  725.71    29.4  724.68    68.5   724.6    88.1  724.08   127.2  722.04
   156.6  719.86   166.4  718.67   176.2  716.13     186  711.52   215.3  693.04
   225.1  688.33   234.9  685.61   244.7  684.47   264.3  683.89     323  684.62
   352.4  684.34   371.9  683.39   391.5  681.78   412.3  678.66   420.9  677.91
   432.3  678.73   469.8  687.08   479.6   690.1   489.4  694.25   538.3  717.34
   557.9  727.04   577.5  737.39   587.3  741.61   655.8  768.29   694.9  781.65
#Mann= 3 , 0 , 0
       0      .1       0   412.3    .045       0   432.3      .1       0
Bank Sta=412.3,432.3
XS Rating Curve= 0 ,0
Exp/Cntr=0.3,0.1

Type RM Length L Ch R = 1 ,9085    ,269.1,263.8,259.2
XS GIS Cut Line= 2
     1751261.622      596452.835       1751293.8      597138.768
#Sta/Elev= 30
       0  748.27    58.9  738.42    88.3  731.63   117.7  723.54   127.5  720.43
   147.2  713.22   166.8  704.39   196.2  689.32     206  684.94   215.8  682.24
   235.4  680.37   296.9  676.21   304.1  675.93   316.9  676.46   343.3   678.9
   372.8  680.59   402.2  681.71   451.2  682.77   461.1  683.63   470.9   686.7
   480.7  692.08   529.7  721.02   549.4   731.7   559.2  736.19   578.8  744.12
   588.6   747.4   598.4  749.64   637.6  756.82   676.9  764.83   686.7  767.35
#Mann= 3 , 0 , 0
       0      .1       0   296.9    .045       0   316.9     .06       0
Bank Sta=296.9,316.9
XS Rating Curve= 0 ,0
Exp/Cntr=0.3,0.1

Type RM Length L Ch R = 1 ,8821.2  ,299.7,301.5,300.9
XS GIS Cut Line= 2
     1750950.751      596534.006     1751118.592       597174.51
#Sta/Elev= 30
       0  787.88     9.7  784.56    19.5  780.81    29.2  776.59    58.4   763.3
    68.2  759.22    97.4  748.19   107.1  743.99   175.3  713.34   233.7  684.98
   243.4  681.13   253.2  678.28   262.9  675.99   270.2  674.84   272.6  674.46
   282.4  674.02   290.2  674.26   399.2  681.78     409  683.04   418.7  685.73
   428.4  689.54   457.6     702   477.1  709.32   486.9  712.35   496.6  714.73
   506.3  716.75   564.8  728.29   574.5  730.39   623.2  741.79   662.1  751.47
#Mann= 3 , 0 , 0
       0      .1       0   270.2    .045       0   290.2     .06       0
Bank Sta=270.2,290.2
XS Rating Curve= 0 ,0
Exp/Cntr=0.3,0.1

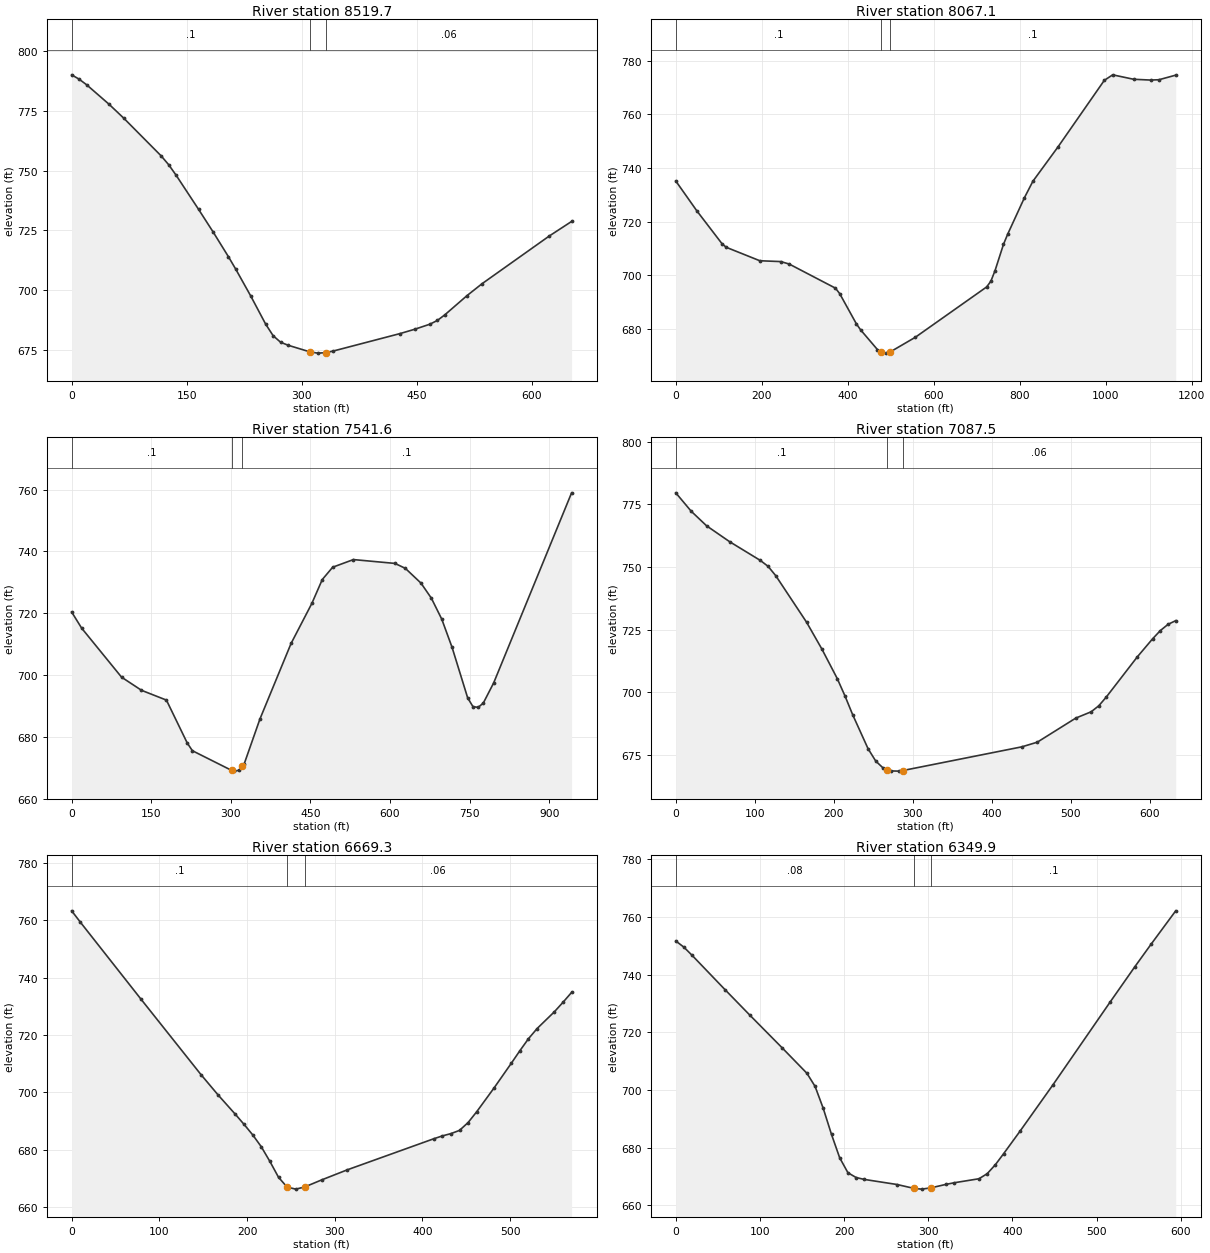
Type RM Length L Ch R = 1 ,8519.7  ,445.2,452.6,460.3
XS GIS Cut Line= 2
     1750677.101      596605.457     1750825.919       597240.59
#Sta/Elev= 30
       0  789.94     9.7  788.13    19.5   785.8    48.7  777.69    68.2  771.78
   116.8  756.11   126.6  752.43   136.3  748.05   165.5  733.86     185  724.16
   204.5  714.08   214.2   708.8   233.7  697.64   253.1  685.94   262.9  681.09
   272.6  678.38   282.4  677.12   311.5  674.29   321.3  673.83   331.5  674.02
   340.8  674.66   428.4  681.98   447.9  683.82   467.3  685.89   477.1  687.46
   486.8  689.78     516  697.87   535.5   702.8   623.1  722.68   652.3  728.77
#Mann= 3 , 0 , 0
       0      .1       0   311.5    .045       0   331.5     .06       0
Bank Sta=311.5,331.5
XS Rating Curve= 0 ,0
Exp/Cntr=0.3,0.1

Type RM Length L Ch R = 1 ,8067.1  ,489.2,525.5,560.8
XS GIS Cut Line= 2
     1750333.334      596489.135     1750264.355      597649.916
#Sta/Elev= 30
       0  735.15    48.9  724.04   107.5  711.78   117.3  710.44   195.4  705.43
   244.3  705.11   263.8   704.2   371.3  695.22   381.1  693.21   420.2  681.87
     430  679.65     469  672.33   478.2  671.33   488.6     671   498.2   671.4
     557  676.89   723.1  695.67   732.9  697.81   742.6  701.77   762.2  711.54
     772  715.34     811  728.94   830.6  735.05   889.2  747.89   996.7  772.65
  1016.2  774.71  1065.1  773.05  1104.2  772.76  1123.7  772.88  1162.8  774.59
#Mann= 3 , 0 , 0
       0      .1       0   478.2    .045       0   498.2      .1       0
Bank Sta=478.2,498.2
XS Rating Curve= 0 ,0
Exp/Cntr=0.3,0.1

Type RM Length L Ch R = 1 ,7541.6  ,481.6,454.1,425.5
XS GIS Cut Line= 3
     1750300.714      596482.544      1750269.06      596658.283
     1749508.115      596722.494
#Sta/Elev= 30
       0   720.4    18.8  715.19      94  699.34   131.6  695.09   178.6  691.92
   217.7  678.09   227.5  675.56   301.7  669.18   305.8  668.96   315.6  669.23
   321.7  670.59   325.4  671.42   354.8   685.8   413.5  710.23   452.7  723.19
   472.3  730.89   491.9  734.88     531  737.35   609.3  736.11   628.9  734.51
   658.3  729.75   677.9  724.87   697.5  718.09     717  708.94   746.4   692.6
   756.2  689.84     766  689.55   775.8  690.97   795.4  697.51   942.2  758.93
#Mann= 3 , 0 , 0
       0      .1       0   301.7    .045       0   321.7      .1       0
Bank Sta=301.7,321.7
XS Rating Curve= 0 ,0
Exp/Cntr=0.3,0.1

Type RM Length L Ch R = 1 ,7087.5  ,413.9,418.2,422.1
XS GIS Cut Line= 2
     1750073.584      596034.735      1749847.65       596626.16
#Sta/Elev= 30
       0  779.58    19.5  772.25      39  766.43    68.2  760.09   107.1  752.62
   116.9  750.26   126.6  746.54   165.6     728   185.1  717.23   204.5   705.5
   214.3  698.56     224   691.1   243.5  677.54   253.2  672.62     263  669.71
   267.6  669.22   272.7  668.68   282.5   668.6   287.6  668.84   438.3  678.29
   457.8  680.14   506.5  689.74     526  692.26   535.7  694.66   545.4  698.23
   584.4  714.14   603.9  721.39   613.6  724.64   623.4  727.14   633.1   728.6
#Mann= 3 , 0 , 0
       0      .1       0   267.6    .045       0   287.6     .06       0
Bank Sta=267.6,287.6
XS Rating Curve= 0 ,0
Exp/Cntr=0.3,0.1

Type RM Length L Ch R = 1 ,6669.3  ,319.4,319.5,319.4
XS GIS Cut Line= 2
     1749711.556      595934.027     1749423.956      596426.232
#Sta/Elev= 30
       0  763.36     9.8  759.44    78.6   732.7   147.4  706.21   167.1  699.04
   186.8  692.29   196.6  688.81   206.4  685.17   216.2  681.02   226.1  675.86
   235.9  670.34   245.7  666.91   255.6  666.21   265.7  666.96     285  669.42
   314.5  672.97   412.8  683.78   422.6  684.78   432.5  685.59   442.3  686.72
   452.1  689.46     462  693.27   481.6   701.5   501.3  710.13   511.1  714.52
   520.9  718.71   530.8  722.28   550.4   728.1   560.2   731.4   570.1  734.88
#Mann= 3 , 0 , 0
       0      .1       0   245.7    .045       0   265.7     .06       0
Bank Sta=245.7,265.7
XS Rating Curve= 0 ,0
Exp/Cntr=0.3,0.1

Type RM Length L Ch R = 1 ,6349.9  ,313.4,316.4,319.1
XS GIS Cut Line= 2
     1749443.441      595762.764      1749143.81      596275.558
#Sta/Elev= 30
       0  751.67     9.7   749.5    19.5  746.65    58.4  734.81    87.6  726.05
   126.6  714.53   155.8  705.77   165.5  701.22   175.2  693.58     185  684.56
   194.7  676.47   204.5  671.28   214.2  669.62   223.9  668.96   262.9  667.19
   283.2  665.83   292.1  665.59   303.2  666.04   321.3  667.26     331  667.81
   360.2  669.19     370  670.96   379.7  674.08   389.4  677.86   408.9  685.67
   447.9   701.7     516  730.49   545.2  742.67   564.7  750.57   593.9  762.12
#Mann= 3 , 0 , 0
       0     .08       0   283.2    .045       0   303.2      .1       0
Bank Sta=283.2,303.2
XS Rating Curve= 0 ,0
Exp/Cntr=0.3,0.1

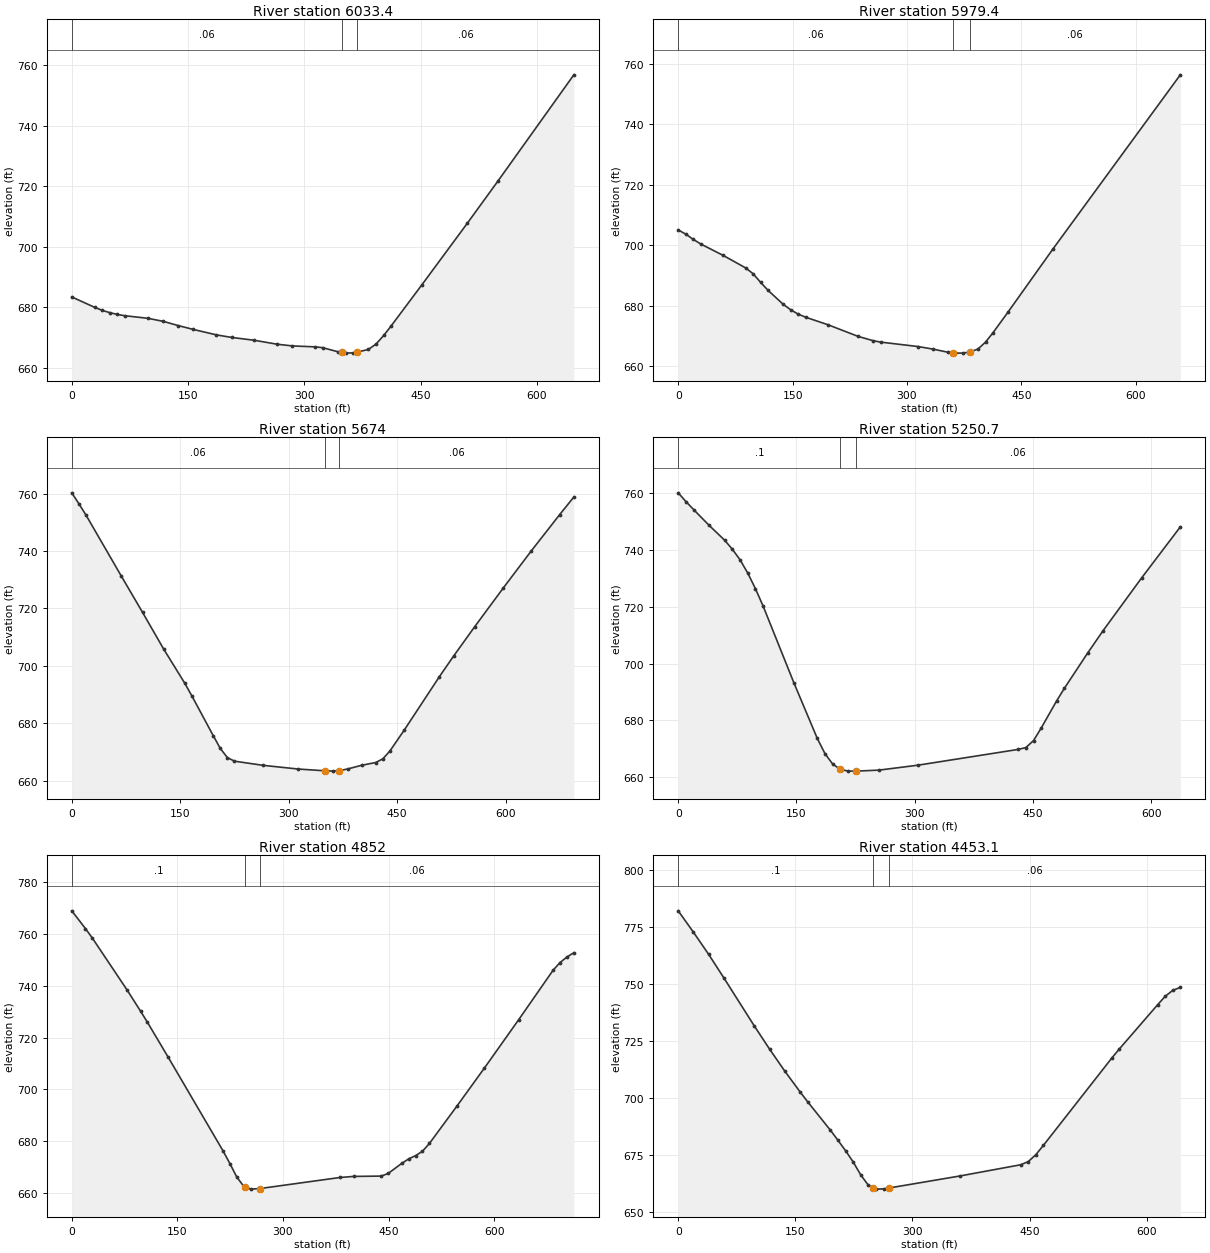
Type RM Length L Ch R = 1 ,6033.4  ,55.3,54,52.8
XS GIS Cut Line= 2
     1749215.744      595609.753     1748830.678      596130.582
#Sta/Elev= 30
       0  683.45    29.4  680.03    39.3  679.01    49.1  678.26    58.9  677.66
    68.7  677.24    98.1   676.4   117.8   675.4   137.4  673.99     157  672.71
   186.5  670.93   206.1  670.09   235.5  669.14     265  667.84   284.6  667.28
     314  666.97   323.9  666.69   343.5  665.34   348.3  665.12   353.3   664.9
   363.1     665   368.3  665.25   382.7  666.12   392.6  667.91   402.4  670.73
   412.2  673.94   451.4  687.36   510.3  707.78   549.6  721.64   647.7  756.77
#Mann= 3 , 0 , 0
       0     .06       0   348.3    .045       0   368.3     .06       0
Bank Sta=348.3,368.3
XS Rating Curve= 0 ,0
Exp/Cntr=0.3,0.1

Type RM Length L Ch R = 1 ,5979.4  ,316.2,305.4,295
XS GIS Cut Line= 2
     1749157.708      595570.753     1748792.152      596118.451
#Sta/Elev= 30
       0  705.04     9.8  703.67    19.7  701.93    29.5   700.4      59  696.61
    88.4  692.48    98.3  690.53   108.1  687.69   117.9  685.03   137.6  680.46
   147.4  678.65   157.2  677.21   167.1  676.17   196.6  673.66   235.9  669.83
   255.5  668.41   265.4  667.94   314.5  666.47   334.2  665.62   353.8  664.58
   359.9   664.4   363.6  664.29   373.5  664.31   382.4 664.663   393.1  665.64
     403  667.92   412.8  671.03   432.4  677.82   491.4  698.73   658.5  756.36
#Mann= 3 , 0 , 0
       0     .06       0   359.9    .045       0   382.4     .06       0
Bank Sta=359.9,382.4
XS Rating Curve= 0 ,0
Exp/Cntr=0.3,0.1

Type RM Length L Ch R = 1 ,5674    ,436.2,423.3,409.9
XS GIS Cut Line= 2
     1748747.517      595382.457     1748624.679      596065.712
#Sta/Elev= 30
       0  760.24     9.8  756.47    19.6  752.53    68.4  731.31    97.8  718.67
   127.1  705.86   156.4  693.93   166.2   689.5   195.6  675.74   205.3  671.32
   215.1  668.12   224.9  666.87     264  665.43   312.9  664.13   349.6  663.52
   361.8   663.4   369.6  663.54   381.3  664.14   400.9  665.44   420.4   666.4
   430.2   667.7     440  670.45   459.6  677.64   508.4  696.31     528  703.46
   557.3  713.72   596.4  727.05   635.5  740.08   674.6  752.66   694.2  758.78
#Mann= 3 , 0 , 0
       0     .06       0   349.6    .045       0   369.6     .06       0
Bank Sta=349.6,369.6
XS Rating Curve= 0 ,0
Exp/Cntr=0.3,0.1

Type RM Length L Ch R = 1 ,5250.7  ,404.3,398.8,392.9
XS GIS Cut Line= 2
     1748209.612      595435.853     1748429.266      596033.729
#Sta/Elev= 30
       0  760.15     9.8  757.06    19.6  754.23    39.2  748.69    58.8  743.48
    68.6   740.3    78.4  736.57    88.2  731.89      98  726.35   107.8   720.2
     147  693.06   176.4  673.67   186.2  668.29     196  664.62   205.8  662.73
   215.6  662.16   225.4  662.14   225.8  662.14   254.8   662.5   303.8  664.22
   431.2  669.78     441  670.43   450.8   672.9   460.6  677.36   480.2  686.93
     490  691.35   519.4  703.71     539   711.6     588  730.22     637  748.15
#Mann= 3 , 0 , 0
       0      .1       0   205.8    .045       0   225.8     .06       0
Bank Sta=205.8,225.8
XS Rating Curve= 0 ,0
Exp/Cntr=0.3,0.1

Type RM Length L Ch R = 1 ,4852    ,396.5,398.9,401
XS GIS Cut Line= 2
     1747772.527      595561.896     1748162.526      596158.954
#Sta/Elev= 30
       0  768.88    19.5  762.02    29.3  758.34    78.2  738.51    97.7   730.2
   107.5  725.89   136.8  712.51   214.9   676.3   224.7  671.38   234.5  666.17
   244.2  662.69   246.7   662.4     254  661.56   266.7  661.76     381  666.05
   400.5  666.46   439.6  666.59   449.4  667.59   468.9  671.52   478.7  673.25
   488.5  674.49   498.2  676.18     508  679.16   547.1  693.58   586.2  708.27
     635  726.96   683.8     746   693.6  748.93   703.4  751.08   713.2  752.72
#Mann= 3 , 0 , 0
       0      .1       0   246.7    .045       0   266.7     .06       0
Bank Sta=246.7,266.7
XS Rating Curve= 0 ,0
Exp/Cntr=0.3,0.1

Type RM Length L Ch R = 1 ,4453.1  ,356.8,357.5,357.4
XS GIS Cut Line= 2
     1747497.809      595761.656     1747802.627      596327.913
#Sta/Elev= 30
       0  782.09    19.5   772.7      39  762.98    58.5  752.64    97.4  731.61
   116.9  721.47   136.4  711.81   155.9  702.74   165.6   698.4   194.9  685.86
   204.6  681.42   214.4  676.82   224.1  671.91   233.8  666.23   243.6  661.67
   249.9  660.59   253.3     660   263.1   660.1   269.9  660.49   360.5  665.75
   438.5  670.68   448.2  672.04     458  675.08   467.7  679.19   555.4  717.53
   565.1  721.53   613.9  740.83   623.6  744.54   633.3  747.17   643.1  748.52
#Mann= 3 , 0 , 0
       0      .1       0   249.9    .045       0   269.9     .06       0
Bank Sta=249.9,269.9
XS Rating Curve= 0 ,0
Exp/Cntr=0.3,0.1

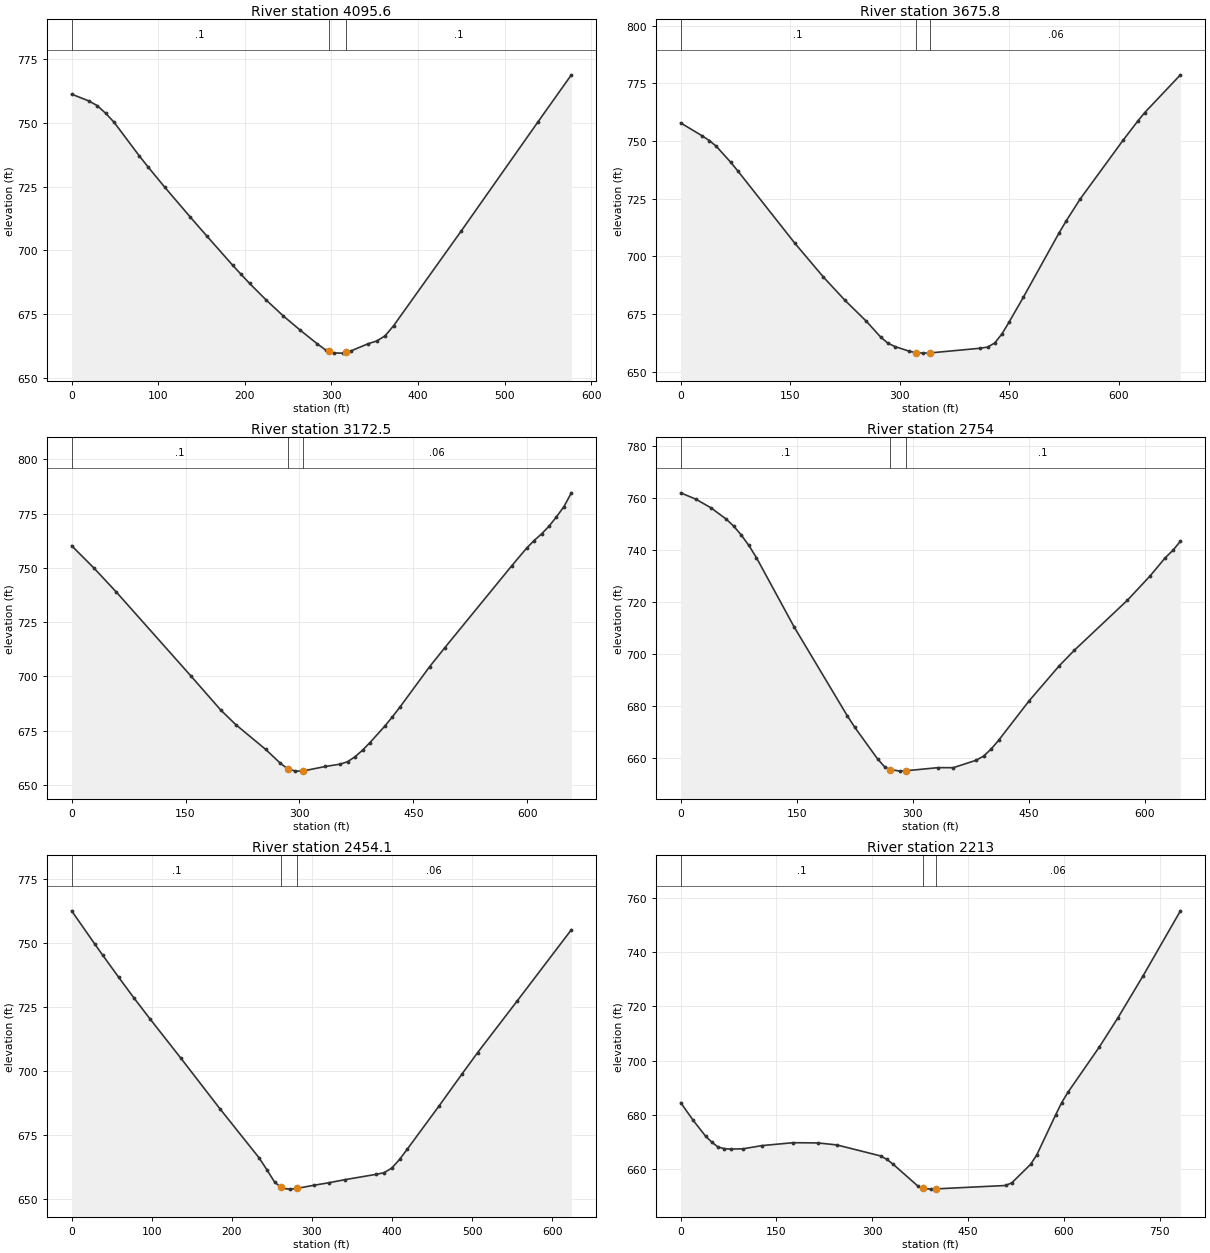
Type RM Length L Ch R = 1 ,4095.6  ,417.1,419.7,422.6
XS GIS Cut Line= 2
     1747220.762       595964.48     1747494.314      596472.655
#Sta/Elev= 30
       0  761.22    19.6   758.6    29.4  756.76    39.1  753.79    48.9  750.25
    78.2  736.98      88  732.79   107.6   724.7   136.9  713.05   156.5  705.43
   185.8  694.17   195.6  690.56   205.4  687.02     225  680.36   244.5   674.2
   264.1  668.61   283.7  663.27   293.4  660.86   296.8  660.46   303.2   659.7
     313  659.64   316.8  659.99   322.8  660.54   342.4  663.33   352.1  664.38
   361.9   666.4   371.7  670.35     450   707.6     538  750.11   577.1  768.81
#Mann= 3 , 0 , 0
       0      .1       0   296.8    .045       0   316.8      .1       0
Bank Sta=296.8,316.8
XS Rating Curve= 0 ,0
Exp/Cntr=0.3,0.1

Type RM Length L Ch R = 1 ,3675.8  ,501.5,503.3,504.8
XS GIS Cut Line= 2
      1746853.67       596019.68     1747093.259      596660.935
#Sta/Elev= 30
       0  757.88    29.3  752.31    39.1  750.26    48.9  747.71    68.5  740.82
    78.2  737.08   156.5  705.64   195.6  690.97   224.9  680.96   254.3  671.83
   273.8  665.02   283.6  662.36   293.4  660.86   312.9  658.84   321.8  658.24
   332.5  657.99   341.8  658.08   410.7  660.13   420.5  660.62   430.3  662.43
   440.1  666.34   449.8  671.43   469.4  682.24   518.3  710.14   528.1  715.37
   547.6  725.03   606.3  750.49   625.9  758.58   635.7  762.38   684.6  778.76
#Mann= 3 , 0 , 0
       0      .1       0   321.8    .045       0   341.8     .06       0
Bank Sta=321.8,341.8
XS Rating Curve= 0 ,0
Exp/Cntr=0.3,0.1

Type RM Length L Ch R = 1 ,3172.5  ,418.5,418.5,418.2
XS GIS Cut Line= 2
     1746445.929      596243.056     1746652.318      596867.941
#Sta/Elev= 30
       0  760.24    29.5   749.9    58.9  738.86   157.2  700.13   196.4  684.46
   216.1  677.76   255.4  666.36     275   659.9   284.4   657.4   294.7  656.31
   304.4  656.35     334  658.45   353.6  659.53   363.4  660.66   373.2  662.94
   383.1  665.98   392.9  669.49   412.5  677.11   422.4  681.36   432.2  685.78
   471.5  704.51   491.1  713.09   579.5  750.97   599.2  759.15     609  762.64
   618.8  765.68   628.6  769.24   638.4  773.52   648.3  778.28   658.1  784.63
#Mann= 3 , 0 , 0
       0      .1       0   284.4    .045       0   304.4     .06       0
Bank Sta=284.4,304.4
XS Rating Curve= 0 ,0
Exp/Cntr=0.3,0.1

Type RM Length L Ch R = 1 ,2754    ,298.3,299.9,301.4
XS GIS Cut Line= 2
     1746053.394      596338.155     1746252.164      596952.591
#Sta/Elev= 30
       0  761.84    19.6  759.39    39.1  756.09    58.7  751.77    68.5  749.06
    78.3  745.63    88.1  741.62    97.8  736.99   146.8  710.23   215.3  676.21
     225  671.78   254.4  659.67   264.2   656.4   270.6  655.56   283.8  654.97
   290.6   655.1   332.7  656.31   352.2  656.29   381.6  659.12   391.4  660.73
   401.2  663.46     411  666.87   450.1  681.91   489.2  695.43   508.8  701.41
   577.3   720.6   606.6  729.93   626.2  736.91     636  739.75   645.8  743.26
#Mann= 3 , 0 , 0
       0      .1       0   270.6    .045       0   290.6      .1       0
Bank Sta=270.6,290.6
XS Rating Curve= 0 ,0
Exp/Cntr=0.3,0.1

Type RM Length L Ch R = 1 ,2454.1  ,240.6,241.1,240.6
XS GIS Cut Line= 2
     1745781.261      596413.023     1745936.232       597017.48
#Sta/Elev= 28
       0  762.56    29.2  749.43      39  745.13    58.5  736.67      78   728.4
    97.5  720.44   136.5  704.88   185.2  685.13     234  665.98   243.8  661.28
   253.5  656.45   261.5  654.42   263.2  653.99     273  653.72   281.5  654.01
   302.2  655.22   321.8  656.25   341.2  657.42   380.2   659.5     390  660.13
   399.8  661.98   409.5  665.35   419.2  669.41   458.3  686.06   487.5  698.78
     507  707.15   555.8   727.1     624  755.18
#Mann= 3 , 0 , 0
       0      .1       0   261.5    .045       0   281.5     .06       0
Bank Sta=261.5,281.5
XS Rating Curve= 0 ,0
Exp/Cntr=0.3,0.1

Type RM Length L Ch R = 1 ,2213    ,296.7,285.2,273.4
XS GIS Cut Line= 2
     1745516.626      596347.244     1745711.019      597105.463
#Sta/Elev= 30
       0   684.5    19.6  677.98    39.1  672.12    48.9  669.91    58.7  668.12
    68.5  667.54    78.3  667.38    97.8  667.49   127.2  668.67   176.1  669.74
   215.2  669.65   244.6  668.92   313.1  664.86   322.9  663.59   332.7  661.81
   371.8  653.68   379.6  652.91   391.4  652.62   399.6  652.71   508.8  653.96
   518.6  654.95   547.9  661.73   557.7  665.24   587.1  679.93   596.8  684.55
   606.6  688.36   655.6  705.01   684.9  715.83     724   731.2   782.7  755.24
#Mann= 3 , 0 , 0
       0      .1       0   379.6    .045       0   399.6     .06       0
Bank Sta=379.6,399.6
XS Rating Curve= 0 ,0
Exp/Cntr=0.3,0.1

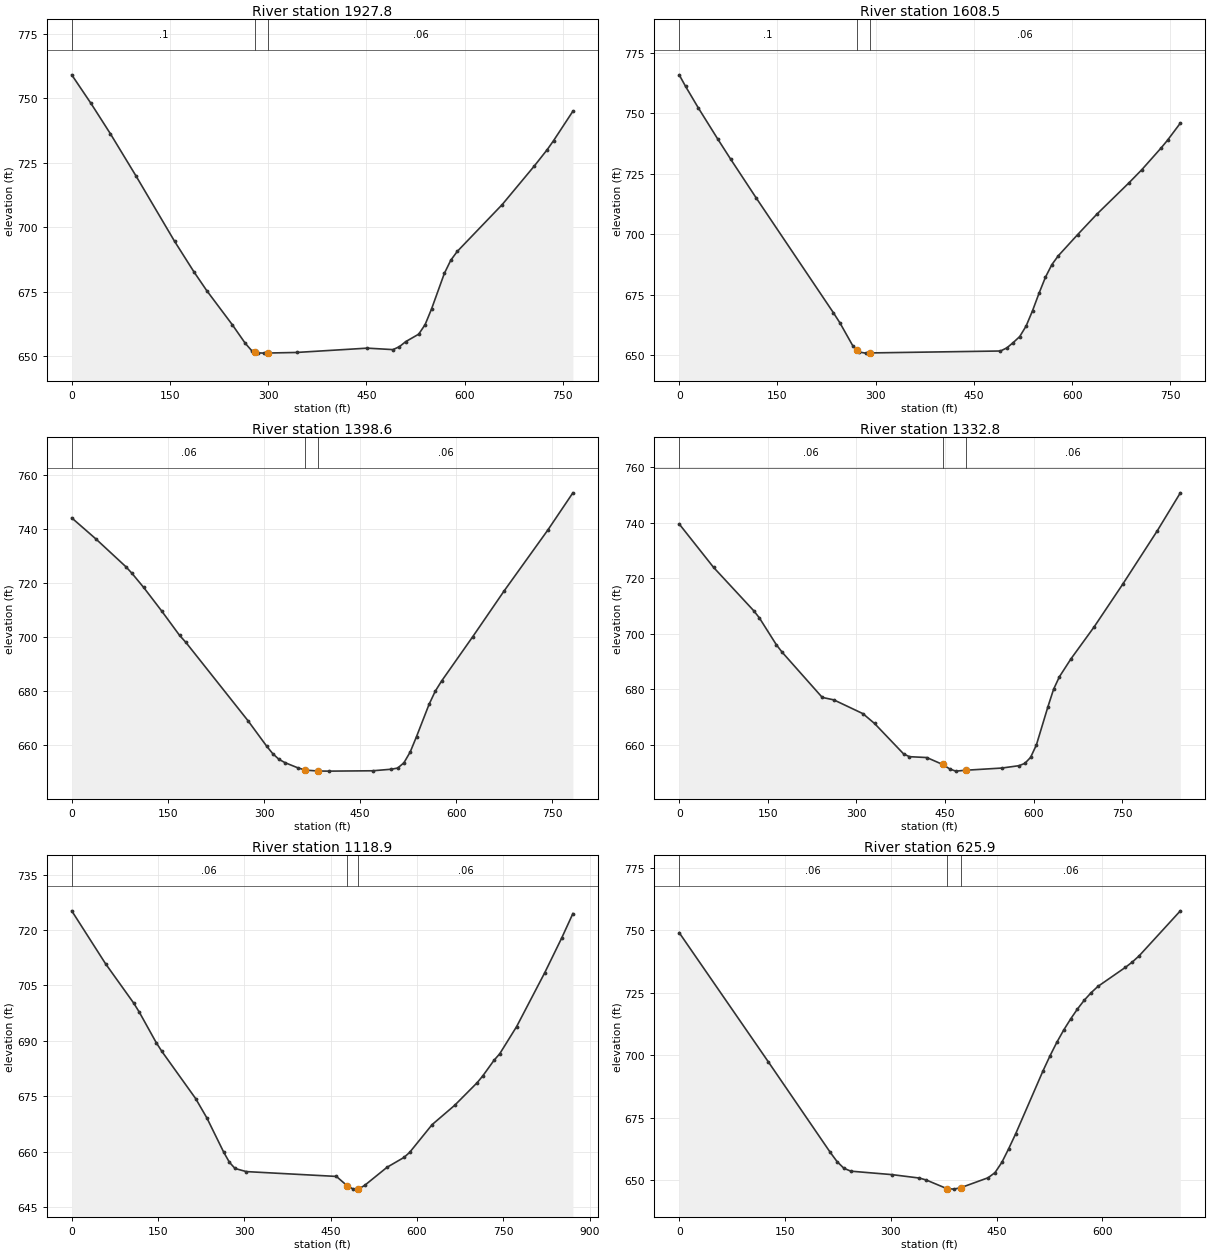
Type RM Length L Ch R = 1 ,1927.8  ,333,319.2,305.5
XS GIS Cut Line= 2
     1745152.158       596562.04     1745643.422      597148.917
#Sta/Elev= 30
       0  759.05    29.4  747.99    58.9   736.3    98.1  719.93     157  694.63
   186.4  682.87   206.1  675.54   245.3  662.28   264.9  655.15   274.7   652.3
   280.2   651.8   284.6   651.4   294.4   651.3   300.2  651.34   343.4  651.56
   451.4  653.23   490.6  652.66   500.4  653.79   510.2  655.77   529.9  658.64
   539.7  662.33   549.5  668.38   569.1  682.17   578.9  687.26   588.7  690.65
   657.4   708.8   706.5  723.76   726.1  730.05   735.9  733.57   765.4  744.96
#Mann= 3 , 0 , 0
       0      .1       0   280.2    .045       0   300.2     .06       0
Bank Sta=280.2,300.2
XS Rating Curve= 0 ,0
Exp/Cntr=0.3,0.1

Type RM Length L Ch R = 1 ,1608.5  ,213.4,210,205.5
XS GIS Cut Line= 2
     1744906.882      596925.277     1745633.136      597166.596
#Sta/Elev= 30
       0   765.9     9.8   761.1    29.4  752.15    58.9  739.37    78.5   731.1
   117.7     715   235.5  667.62   245.3   663.5   264.9  654.07   271.2  652.35
   274.7   651.4   284.5  650.94   291.2  651.02   490.6  651.82   500.4  653.12
   510.2  655.33     520  657.78   529.8  662.15   539.6  668.49   549.4  675.61
   559.3  682.31   569.1  687.51   578.9  691.15   608.3  699.86   637.8  708.34
   686.8  721.28   706.4   726.7   735.9  735.69   745.7  738.89   765.3  745.96
#Mann= 3 , 0 , 0
       0      .1       0   271.2    .045       0   291.2     .06       0
Bank Sta=271.2,291.2
XS Rating Curve= 0 ,0
Exp/Cntr=0.3,0.1

Type RM Length L Ch R = 1 ,1398.6  ,65.8,65.8,65.8
XS GIS Cut Line= 4
     1744860.746      597120.524     1744979.368      597240.093
     1745152.197      597217.442      1745585.05      597292.198
#Sta/Elev= 30
       0  744.06    37.4  736.34    84.2  726.07    93.6  723.68   112.3  718.33
   140.4  709.63   168.4  700.59   178.1  698.04     275  669.09     304  659.73
   313.7  656.89   323.4  654.79     333  653.55   352.5  651.69   364.5  650.82
   384.5  650.48   401.3  650.44   469.6  650.57   498.9  651.15   508.7  651.58
   518.4  653.54   528.2  657.54     538   663.2   557.5  675.08   567.2  679.97
     577   683.7   625.8  700.16   674.6  717.02     743   739.6     782  753.32
#Mann= 3 , 0 , 0
       0     .06       0   364.5    .045       0   384.5     .06       0
Bank Sta=364.5,384.5
XS Rating Curve= 0 ,0
Exp/Cntr=0.3,0.1

Type RM Length L Ch R = 1 ,1332.8  ,198.8,213.8,226.8
XS GIS Cut Line= 4
     1744785.113      597137.482     1744955.666      597309.397
     1745150.846      597283.816     1745554.437      597353.519
#Sta/Elev= 30
       0  739.62    58.1  723.99   125.9   708.4   135.6   705.8   164.7     696
   174.4  693.35   242.2  677.07   261.8  676.18   311.1  671.21   330.8  667.66
     380  656.69   389.8  655.69   419.3  655.38   445.9652.9008   458.5  651.23
   468.3  650.48   485.9650.8102   546.3  651.59   575.5  652.45   585.3  653.28
     595  655.44   604.8  659.91   624.3  673.66     634  680.04   643.8  684.52
   663.3  690.96   702.3  702.41   751.1  717.92   809.6  737.19   848.6  750.85
#Mann= 3 , 0 , 0
       0     .06       0   445.9    .045       0   485.9     .06       0
Bank Sta=445.9,485.9
XS Rating Curve= 0 ,0
Exp/Cntr=0.3,0.1

Type RM Length L Ch R = 1 ,1118.9  ,480.4,493,512.4
XS GIS Cut Line= 2
     1744768.648      597178.802     1745431.514      597743.563
#Sta/Elev= 30
       0  725.21    58.7   710.9   107.6  700.24   117.4  697.78   146.8  689.52
   156.6  687.15   215.3  674.37   234.8  669.13   264.2  659.81     274  657.11
   283.8  655.43   303.3  654.59   459.9  653.28   478.1  650.82   489.2  649.84
   498.1  649.86   508.8  650.83   547.9  655.76   577.3  658.42   587.1  659.78
   626.2  667.31   665.4  672.54   704.5  678.67   714.3  680.52   733.8  684.74
   743.6  686.48     773  693.85   821.9  708.45   851.3  717.83   870.8  724.47
#Mann= 3 , 0 , 0
       0     .06       0   478.1    .045       0   498.1     .06       0
Bank Sta=478.1,498.1
XS Rating Curve= 0 ,0
Exp/Cntr=0.3,0.1

Type RM Length L Ch R = 1 ,625.9   ,447.1,438.7,423.1
XS GIS Cut Line= 2
     1744688.667      597134.498     1744743.962      597842.955
#Sta/Elev= 30
       0  749.02   126.6  697.27   214.2  661.16   223.9  657.45   233.6  654.79
   243.4  653.64   301.8  652.26   340.7  650.88   350.4   650.1   379.3  646.69
   389.4  646.46   399.3  647.04     438  651.01   447.8  653.06   457.5  657.17
   467.2  662.63     477  668.53   515.9  693.79   525.7  699.72   535.4  705.15
   545.1  710.03   554.9  714.45   564.6  718.46   574.3  721.99   584.1  725.01
   593.8  727.54   632.7  735.15   642.5  737.28   652.2  739.76   710.6  757.75
#Mann= 3 , 0 , 0
       0     .06       0   379.3    .045       0   399.3     .06       0
Bank Sta=379.3,399.3
XS Rating Curve= 0 ,0
Exp/Cntr=0.3,0.1

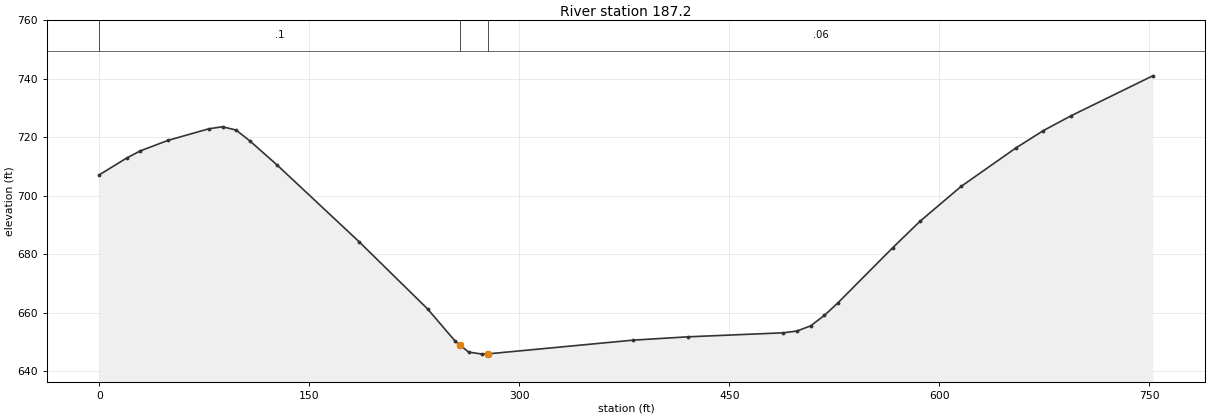
Type RM Length L Ch R = 1 ,187.2   ,187.2,187.2,186.7
XS GIS Cut Line= 2
     1744159.108      597330.961     1744648.153      597902.821
#Sta/Elev= 30
       0   707.2    19.5  712.93    29.3  715.39    48.9  718.95    78.2  722.93
      88  723.63    97.7   722.5   107.5   718.8     127  710.55   185.7  684.26
   234.5  661.35   254.1  650.39   257.9  648.91   263.8   646.6   273.6   645.9
   277.9     646   381.1  650.67   420.2  651.81   488.6  653.19   498.4   653.8
   508.2  655.59   517.9  659.13   527.7  663.47   566.8   682.3   586.3  691.34
   615.6  703.23   654.7  716.37   674.3   722.3   693.8   727.3   752.5  741.04
#Mann= 3 , 0 , 0
       0      .1       0   257.9    .045       0   277.9     .06       0
Bank Sta=257.9,277.9
XS Rating Curve= 0 ,0
Exp/Cntr=0.3,0.1